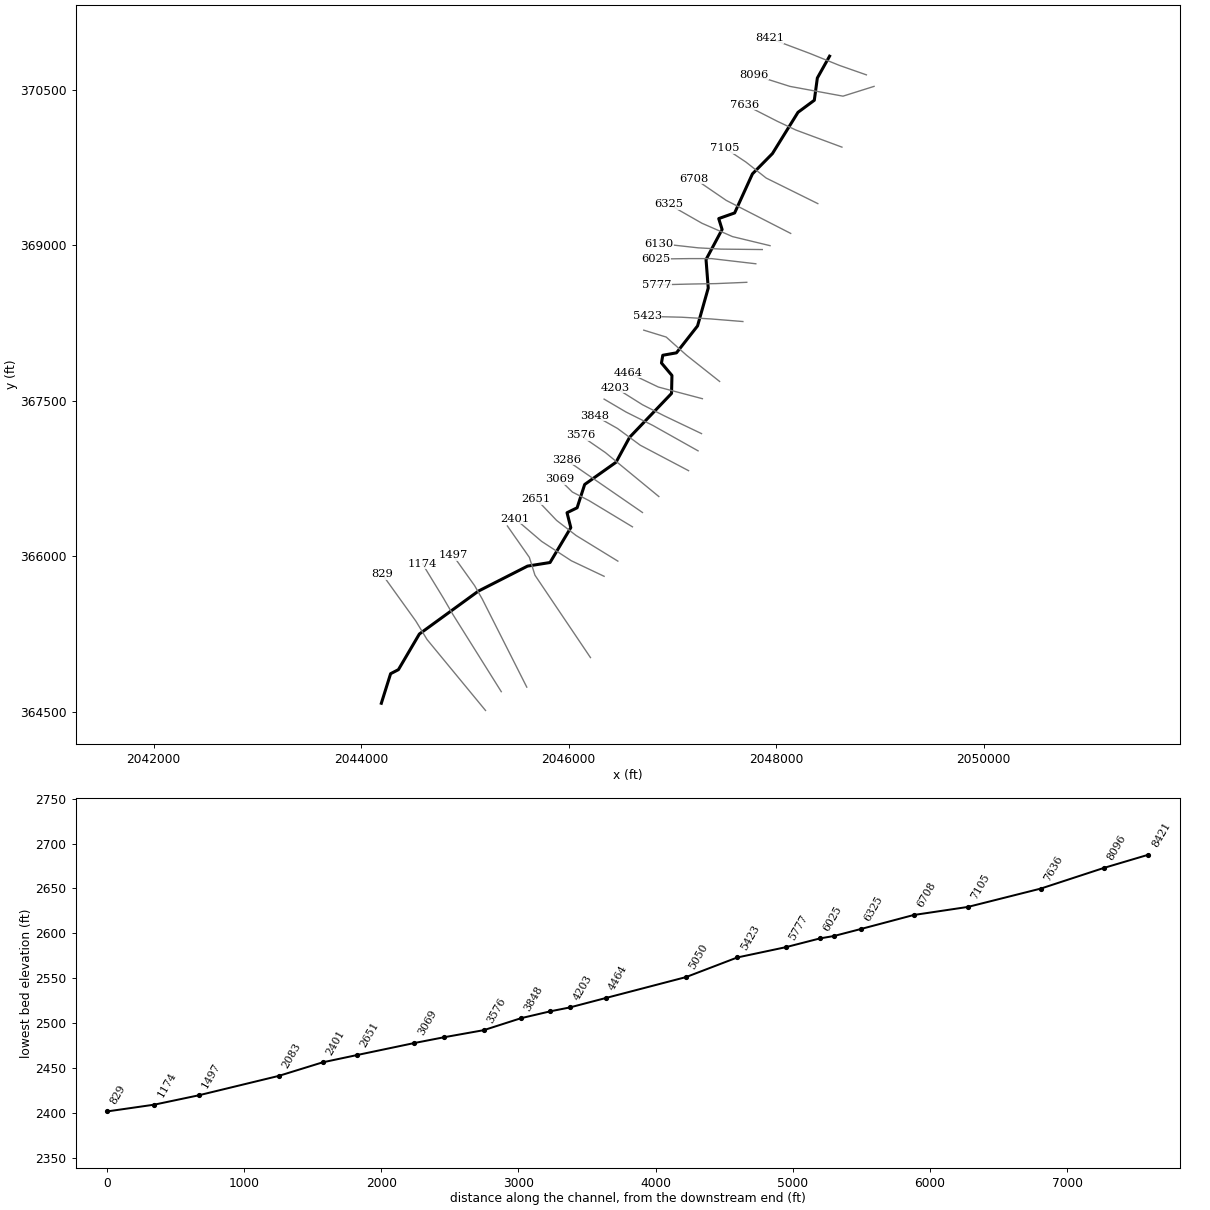
--- LAURELCK1.prj (project) ---

Proj Title=LAURELCK1
Current Plan=p01
Default Exp/Contr=0,0
English Units
Geom File=g01
Flow File=f01
Plan File=p01
Background Map Layer=DPs_HMS_shifted
Background Map Layer=QC_TUCKHORN
BEGIN DESCRIPTION:
Stream Name- Laurel Creek 1
Flood Zone: Zone A
Greenbrier County, WV
County-Wide Study
WVDHSEM-2018-3, Flood Risk Project
HEC-RAS Version: 5.0.7
General Notes:
For the Hydrology Regression was used.
END DESCRIPTION:
DSS File=dss
DSS Export Rating Curves= 0
DSS Export Rating Curve Sorted= 0
DSS Export Volume Flow Curves= 0
DXF Filename=..\..\H1\MEADOWRV4\MEADOWRV4.
DXF OffsetX= 0
DXF OffsetY= 0
DXF ScaleX= 0
DXF ScaleY= 0

--- LAURELCK1.p01 (plan) ---

Plan Title=Floodplain
Program Version=5.07
Short Identifier=Floodplain
Geom File=g01
Flow File=f01
Subcritical Flow
K Sum by GR= 0
Std Step Tol= 0.01
Critical Tol= 0.01
Num of Std Step Trials= 20
Max Error Tol= 0.3
Flow Tol Ratio= 0.001
Split Flow NTrial= 30
Split Flow Tol= 0.02
Split Flow Ratio= 0.02
Log Output Level= 0
Friction Slope Method= 1
Unsteady Friction Slope Method= 2
Unsteady Bridges Friction Slope Method= 1
Parabolic Critical Depth
Global Vel Dist= 0 , 0 , 0
Global Log Level= 0
CheckData=False
Encroach Param=-1 ,0,0, 0
Computation Interval=0.1SEC
Output Interval=1MIN
Instantaneous Interval=Max Profile
Mapping Interval=1HOUR
Computation Time Step Use Courant=        0
Computation Time Step Use Time Series=    0
Computation Time Step Count To Double=0
Computation Time Step Max Doubling=0
Computation Time Step Max Halving=0
Computation Time Step Residence Courant=0
Run HTab= 0
Run UNet= 0
Run Sediment= 0
Run PostProcess= 0
Run WQNet= 0
Run RASMapper= 0
UNET Theta= 0
UNET Theta Warmup= 0
UNET ZTol= 0
UNET ZSATol= 0
UNET MxIter= 0
UNET Max Iter WO Improvement= 0
UNET MaxInSteps= 0
UNET DtIC= 0
UNET DtMin= 0
UNET MaxCRTS= 0
UNET WFStab= 0
UNET SFStab= 0
UNET WFX= 1
UNET SFX= 1
UNET 1D Methodology=Finite Difference
UNET DSS MLevel= 1
UNET Pardiso=0
UNET DZMax Abort= 0
UNET Use Existing IB Tables= 0
UNET Froude Reduction=False
UNET Froude Limit= 0
UNET Froude Power= 0
UNET D1 Cores= 0
UNET D2 Coriolis=0
UNET D2 Cores= 0
UNET D2 Theta= 1
UNET D2 Theta Warmup= 1
UNET D2 Z Tol= 0.01
UNET D2 Volume Tol= 0.01
UNET D2 Max Iterations= 20
UNET D2 Equation= 0
UNET D2 RampUpFraction=0.1
UNET D2 TimeSlices= 1
UNET D2 BCVolumeCheck=0
UNET D1D2 MaxIter= 0
UNET D1D2 ZTol=0.01
UNET D1D2 QTol=0.1
UNET D1D2 MinQTol=1
DSS File=dss
Write IC File= 0
Write IC File at Fixed DateTime=0
Write IC File at Sim End=0
Echo Input=False
Echo Parameters=False
Echo Output=False
Write Detailed= 0
HDF Write Warmup=0
HDF Write Time Slices=0
HDF Flush=0
HDF Face Node Velocities=0
HDF Compression= 1
HDF Chunk Size= 1
HDF Spatial Parts= 1
HDF Use Max Rows=0
HDF Fixed Rows= 1
Calibration Method= 0
Calibration Iterations= 20
Calibration Max Change=0.05
Calibration Tolerance=0.2
Calibration Maximum=1.5
Calibration Minimum=0.5
Calibration Optimization Method= 1
WQ AD Non Conservative
WQ ULTIMATE=-1
WQ Max Comp Step=1HOUR
WQ Output Interval=15MIN
WQ Output Selected Increments= 0
WQ Output face flow=0
WQ Output face velocity=0
WQ Output face area=0
WQ Output face dispersion=0
WQ Output cell volume=0
WQ Output cell surface area=0
WQ Output cell continuity=0
WQ Output cumulative cell continuity=0
WQ Output face conc=0
WQ Output face dconc_dx=0
WQ Output face courant=0
WQ Output face peclet=0
WQ Output face adv mass=0
WQ Output face disp mass=0
WQ Output cell mass=0
WQ Output cell source sink temp=0
WQ Output nsm pathways=0
WQ Output nsm derived pathways=0
WQ Output MaxMinRange=-1
WQ Daily Max Min Mean=-1
WQ Daily Range=0
WQ Daily Time=0
WQ Create Restart=0
WQ Fixed Restart=0
WQ System Summary=0
WQ Write To DSS=0
WQ Use Fixed Temperature=0
Sorting and Armoring Iterations= 10
XS Update Threshold= 0.02
Bed Roughness Predictor= 0
Hydraulics Update Threshold= 0.02
Energy Slope Method= 1
Volume Change Method= 1
Sediment Retention Method= 0
XS Weighting Method= 0
Number of US Weighted Cross Sections= 1
Number of DS Weighted Cross Sections= 1
Upstream XS Weight=0
Main XS Weight=1
Downstream XS Weight=0
Number of DS XS's Weighted with US Boundary= 1
Upstream Boundary Weight= 1
Weight of XSs Associated with US Boundary= 0
Number of US XS's Weighted with DS Boundary= 1
Downstream Boundary Weight= 0.5
Weight of XSs Associated with DS Boundary= 0.5
Percentile Method= 0
Sediment Output Level= 3
Mass or Volume Output= 0
Output Increment Type= 1
Profile and TS Output Increment= 1
XS Output Flag= 0
XS Output Increment= 10
Write Gradation File= 0
Read Gradation Hotstart= 0
Write HDF5 File= 1
Write Binary Output= 1
Write DSS Sediment File= 0
SV Curve= 0
Specific Gage Flag= 0

--- LAURELCK1.f01 (steady flow) ---

Flow Title=LAURELCK1
Program Version=5.07
Number of Profiles= 6
Profile Names=f1p,f10p,f4p,f2p,f02p,f1pplus
River Rch & RM=BROADRN,Main            ,3339
     761     339     488     619    1150     917
River Rch & RM=LAURELBR,Main            ,3440
     558     218     334     440     888     691
River Rch & RM=LAURELCK1,Main            ,8421
     526     277     369     445     736     778
River Rch & RM=LAURELCK1,Main            ,7636
     821     440     581     697    1140    1210
River Rch & RM=LAURELCK1,Main            ,6025
     949     512     674     807    1310    1400
River Rch & RM=LAURELCK1,Main            ,2083
    1180     639     838    1000    1620    1740
River Rch & RM=MLGNCK,Main            ,43088
    1400     765    1000    1190    1920    2070
River Rch & RM=MLGNCK,Main            ,41997
    1560     858    1120    1330    2140    2310
River Rch & RM=MLGNCK,Main            ,35646
    1910    1060    1370    1630    2610    2820
River Rch & RM=MLGNCK,Main            ,34400
    2210    1230    1600    1890    3010    3270
River Rch & RM=MLGNCK,Main            ,29681
    3770    2150    2750    3250    5090    5580
River Rch & RM=MLGNCK,Main            ,25204
    4210    2400    3080    3630    5670    6230
River Rch & RM=MLGNCK,Main            ,13347
    4770    2730    3490    4110    6400    7050
River Rch & RM=MLGNCKTR3,Main            ,13516
    1790     990    1290    1530    2450    2650
River Rch & RM=MLGNCKTR3,Main            ,9632
    2060    1140    1480    1760    2810    3040
River Rch & RM=MLGNCKTR4,Main            ,3322
     500     263     350     423     700     739
River Rch & RM=MLGNCKTR4,Main            ,2737
     557     294     391     471     778     823
River Rch & RM=TUCKHORN,Main            ,14873
     566     299     398     479     791     837
River Rch & RM=TUCKHORN,Main            ,12657
     639     339     450     542     891     945
River Rch & RM=TUCKHORN,Main            ,10275
    1150     622     817     976    1580    1700
River Rch & RM=TUCKHORN,Main            ,6291
    1390     758     991    1180    1900    2050
River Rch & RM=TUCKHORN,Main            ,4342
    1770     980    1280    1520    2430    2620
River Rch & RM=TUCKHORN,Main            ,346
    2140    1190    1540    1830    2910    3160
River Rch & RM=TUCKHORN,Main            ,239
    3116    1352    1964    2514    3780    4764
River Rch & RM=TUCKHORNT2,Main            ,1848
     570     301     400     482     796     842
Boundary for River Rch & Prof#=BROADRN,Main            , 1
Up Type= 0
Dn Type= 3
Dn Slope=0.05922
Boundary for River Rch & Prof#=BROADRN,Main            , 2
Up Type= 0
Dn Type= 3
Dn Slope=0.05922
Boundary for River Rch & Prof#=BROADRN,Main            , 3
Up Type= 0
Dn Type= 3
Dn Slope=0.05922
Boundary for River Rch & Prof#=BROADRN,Main            , 4
Up Type= 0
Dn Type= 3
Dn Slope=0.05922
Boundary for River Rch & Prof#=BROADRN,Main            , 5
Up Type= 0
Dn Type= 3
Dn Slope=0.05922
Boundary for River Rch & Prof#=BROADRN,Main            , 6
Up Type= 0
Dn Type= 3
Dn Slope=0.05922
Boundary for River Rch & Prof#=LAURELBR,Main            , 1
Up Type= 0
Dn Type= 3
Dn Slope=0.04145
Boundary for River Rch & Prof#=LAURELBR,Main            , 2
Up Type= 0
Dn Type= 3
Dn Slope=0.04145
Boundary for River Rch & Prof#=LAURELBR,Main            , 3
Up Type= 0
Dn Type= 3
Dn Slope=0.04145
Boundary for River Rch & Prof#=LAURELBR,Main            , 4
Up Type= 0
Dn Type= 3
Dn Slope=0.04145
Boundary for River Rch & Prof#=LAURELBR,Main            , 5
Up Type= 0
Dn Type= 3
Dn Slope=0.04145
Boundary for River Rch & Prof#=LAURELBR,Main            , 6
Up Type= 0
Dn Type= 3
Dn Slope=0.04145
Boundary for River Rch & Prof#=LAURELCK1,Main            , 1
Up Type= 0
Dn Type= 3
Dn Slope=0.009
Boundary for River Rch & Prof#=LAURELCK1,Main            , 2
Up Type= 0
Dn Type= 3
Dn Slope=0.009
Boundary for River Rch & Prof#=LAURELCK1,Main            , 3
Up Type= 0
Dn Type= 3
Dn Slope=0.009
Boundary for River Rch & Prof#=LAURELCK1,Main            , 4
Up Type= 0
Dn Type= 3
Dn Slope=0.009
Boundary for River Rch & Prof#=LAURELCK1,Main            , 5
Up Type= 0
Dn Type= 3
Dn Slope=0.009
Boundary for River Rch & Prof#=LAURELCK1,Main            , 6
Up Type= 0
Dn Type= 3
Dn Slope=0.009
Boundary for River Rch & Prof#=MLGNCK,Main            , 1
Up Type= 0
Dn Type= 3
Dn Slope=0.0302
Boundary for River Rch & Prof#=MLGNCK,Main            , 2
Up Type= 0
Dn Type= 3
Dn Slope=0.0302
Boundary for River Rch & Prof#=MLGNCK,Main            , 3
Up Type= 0
Dn Type= 3
Dn Slope=0.0302
Boundary for River Rch & Prof#=MLGNCK,Main            , 4
Up Type= 0
Dn Type= 3
Dn Slope=0.0302
Boundary for River Rch & Prof#=MLGNCK,Main            , 5
Up Type= 0
Dn Type= 3
Dn Slope=0.0302
Boundary for River Rch & Prof#=MLGNCK,Main            , 6
Up Type= 0
Dn Type= 3
Dn Slope=0.0302
Boundary for River Rch & Prof#=MLGNCKTR3,Main            , 1
Up Type= 0
Dn Type= 3
Dn Slope=0.00395
Boundary for River Rch & Prof#=MLGNCKTR3,Main            , 2
Up Type= 0
Dn Type= 3
Dn Slope=0.00395
Boundary for River Rch & Prof#=MLGNCKTR3,Main            , 3
Up Type= 0
Dn Type= 3
Dn Slope=0.00395
Boundary for River Rch & Prof#=MLGNCKTR3,Main            , 4
Up Type= 0
Dn Type= 3
Dn Slope=0.00395
Boundary for River Rch & Prof#=MLGNCKTR3,Main            , 5
Up Type= 0
Dn Type= 3
Dn Slope=0.00395
Boundary for River Rch & Prof#=MLGNCKTR3,Main            , 6
Up Type= 0
Dn Type= 3
Dn Slope=0.00395
Boundary for River Rch & Prof#=MLGNCKTR4,Main            , 1
Up Type= 0
Dn Type= 3
Dn Slope=0.01609
Boundary for River Rch & Prof#=MLGNCKTR4,Main            , 2
Up Type= 0
Dn Type= 3
Dn Slope=0.01609
Boundary for River Rch & Prof#=MLGNCKTR4,Main            , 3
Up Type= 0
Dn Type= 3
Dn Slope=0.01609
Boundary for River Rch & Prof#=MLGNCKTR4,Main            , 4
Up Type= 0
Dn Type= 3
Dn Slope=0.01609
Boundary for River Rch & Prof#=MLGNCKTR4,Main            , 5
Up Type= 0
Dn Type= 3
Dn Slope=0.01609
Boundary for River Rch & Prof#=MLGNCKTR4,Main            , 6
Up Type= 0
Dn Type= 3
Dn Slope=0.01609
Boundary for River Rch & Prof#=TUCKHORN,Main            , 1
Up Type= 0
Dn Type= 1
Dn Known WS=2122.5
Boundary for River Rch & Prof#=TUCKHORN,Main            , 2
Up Type= 0
Dn Type= 1
Dn Known WS=2120.48
Boundary for River Rch & Prof#=TUCKHORN,Main            , 3
Up Type= 0
Dn Type= 1
Dn Known WS=2121.09
Boundary for River Rch & Prof#=TUCKHORN,Main            , 4
Up Type= 0
Dn Type= 1
Dn Known WS=2121.64
Boundary for River Rch & Prof#=TUCKHORN,Main            , 5
Up Type= 0
Dn Type= 1
Dn Known WS=2123.27
Boundary for River Rch & Prof#=TUCKHORN,Main            , 6
Up Type= 0
Dn Type= 1
Dn Known WS=2124.99
Boundary for River Rch & Prof#=TUCKHORNT2,Main            , 1
Up Type= 0
Dn Type= 3
Dn Slope=0.02818
Boundary for River Rch & Prof#=TUCKHORNT2,Main            , 2
Up Type= 0
Dn Type= 3
Dn Slope=0.02818
Boundary for River Rch & Prof#=TUCKHORNT2,Main            , 3
Up Type= 0
Dn Type= 3
Dn Slope=0.02818
Boundary for River Rch & Prof#=TUCKHORNT2,Main            , 4
Up Type= 0
Dn Type= 3
Dn Slope=0.02818
Boundary for River Rch & Prof#=TUCKHORNT2,Main            , 5
Up Type= 0
Dn Type= 3
Dn Slope=0.02818
Boundary for River Rch & Prof#=TUCKHORNT2,Main            , 6
Up Type= 0
Dn Type= 3
Dn Slope=0.02818
DSS Import GetInterval= 0
DSS Import GetPeak= 0
DSS Import FillOption= 0

--- LAURELCK1.g01 (geometry) ---

Geom Title=MasterGeometry
Program Version=5.07

River Reach=LAURELCK1       ,Main
Reach XY= 30
2048514.88000001370821.791000009     2048397.094370611.613000005
2048367.80999999370396.9060000032048210.48400001370280.591999993
2047964.24800001369883.054000005     2047771.392369687.268000007
2047599.75800003369310.6930000042047446.42099999369256.283000007
2047478.98799999369151.3810000122047324.09600003368861.493000001
2047345.33700003368586.5950000142047242.27299999368221.640000016
2047039.10300003367962.2839999942046907.17999999367938.797000021
2046894.52300002367864.3160000152046995.48800002367744.207000017
2046991.62699999      367570.9632046587.33400004367148.067000002
2046456.56200002366907.6400000012046154.22899999366693.214000002
2046081.30700003366468.5380000172045984.19500001366421.056999996
     2046020.483366277.0820000172045820.37400003365941.143000022
2045603.29900004365906.476999998     2045129.369365665.270999998
2044560.82900004365251.9399999982044359.05499999364908.503999993
2044283.64600001364869.3170000022044194.21492054 364584.43658267

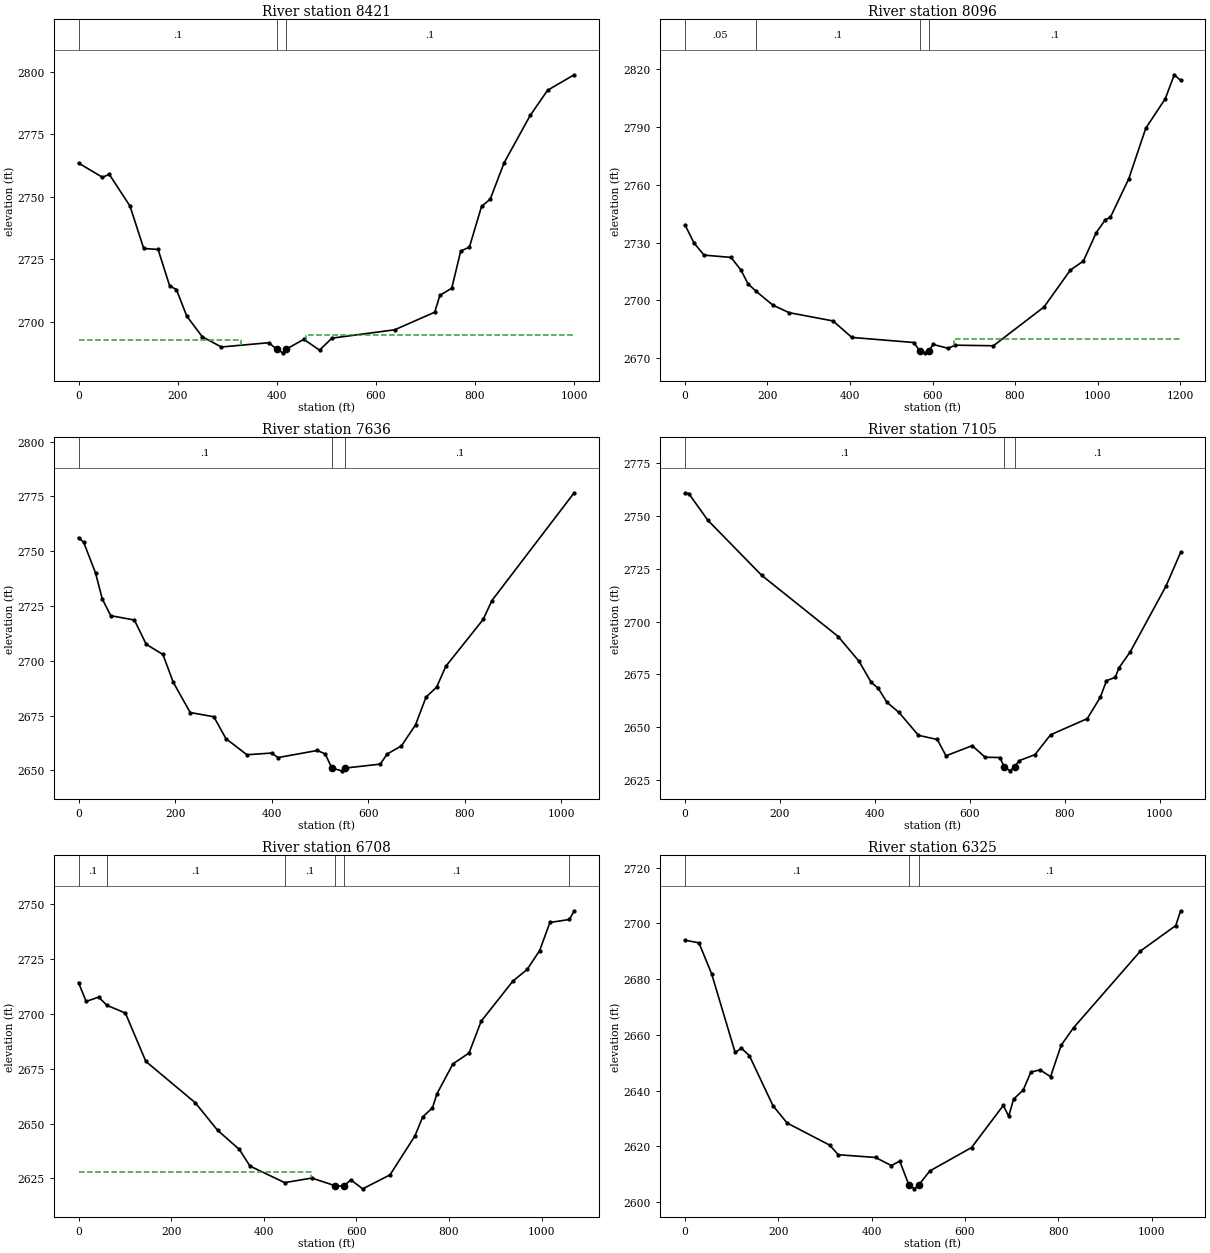
Type RM Length L Ch R = 1 ,8421    ,324.7,324.7,324.7
XS GIS Cut Line= 4
2048869.71150722370641.7021604882048610.56486792370732.571761282
2048327.85944323370847.0001474662047934.09117313370995.083941352
#Sta/Elev= 30
       0 2763.48    48.2 2757.78    62.1 2758.94   103.8 2746.29   131.6 2729.29
   160.6  2728.9   183.8  2714.4   197.7 2712.82   218.5 2702.22   249.8 2693.97
   288.3 2689.88   383.9 2691.59  400.062689.013   412.2 2687.54   418.9 2688.98
   454.7 2692.94   486.5 2688.61   511.3 2693.41   638.1 2696.76   718.8 2703.79
   729.3 2710.56   753.2 2713.37   771.3 2728.22   788.9 2729.87   813.4 2746.12
   830.9 2749.03     859 2763.61   911.6 2782.52   946.6 2792.581000.295 2798.78
#Mann= 3 ,-1 , 0
       0      .1       0  400.06    .045       0   418.9      .1       0
#XS Ineff= 2 , 0
          327.27  2692.7  458.18         2694.86
Permanent Ineff=
       F       F
Bank Sta=400.06,418.9
XS Rating Curve= 0 ,0
Exp/Cntr(USF)=0,0
Exp/Cntr=0.3,0.1

Type RM Length L Ch R = 1 ,8096    ,460,460,460
XS GIS Cut Line= 4
2048943.75340417370530.6393150742048644.22027562 370436.40417351
2048132.65807856370530.6393150742047782.64183847370641.702160488
#Sta/Elev= 30
       0 2739.21    21.9 2729.82    46.2 2723.51   111.5 2722.33   135.6 2715.79
   152.7 2708.69     1712704.982   212.9 2697.59   252.5 2693.65   358.8 2689.37
   404.5  2680.8   554.6 2678.17  568.462673.971   581.3 2672.81  591.532673.971
   601.3 2677.18     638 2675.15   654.6 2676.78   747.6 2676.49   870.3 2696.61
   934.1 2715.75   965.7 2720.43   996.8 2735.15  1019.1 2741.94  1031.1  2743.1
  1075.8  2763.2    1117 2789.41  1164.1 2804.64    1186 2817.091201.391 2814.15
#Mann= 4 ,-1 , 0
       0     .05       0     171      .1       0  568.46    .045       0
  591.53      .1       0
#XS Ineff= 2 , 0
                          652.12         2679.82
Permanent Ineff=
       F       F
Bank Sta=568.46,591.53
XS Rating Curve= 0 ,0
Exp/Cntr(USF)=0,0
Exp/Cntr=0.3,0.1

Type RM Length L Ch R = 1 ,7636    ,531.4,531.4,531.4
XS GIS Cut Line= 4
2048634.12365331369945.0352210712048189.87227166370109.946718808
2048011.49861084370194.0852380612047695.13777845370355.631195027
#Sta/Elev= 30
       0 2756.17    10.7 2754.01    35.2 2740.09    49.2  2728.2    66.7 2720.55
   115.7 2718.58   140.2  2707.5   174.8 2702.85   196.2 2690.18   231.2 2676.38
   280.2 2674.45   305.2 2664.48   348.6 2657.12   399.7 2657.89   413.1 2655.84
   494.3 2659.06   510.7 2657.52  524.582651.048   545.1 2649.78  552.522651.048
   624.9 2652.85   638.8  2657.4   668.7 2661.19   697.9 2670.77   719.6 2683.42
   741.6 2687.99   760.5 2697.45   837.9 2718.84     856 2727.461026.314 2776.62
#Mann= 3 ,-1 , 0
       0      .1       0  524.58    .045       0  552.52      .1       0
Bank Sta=524.58,552.52
XS Rating Curve= 0 ,0
Exp/Cntr(USF)=0,0
Exp/Cntr=0.3,0.1

Type RM Length L Ch R = 1 ,7105    ,396.2,396.2,396.2
XS GIS Cut Line= 4
 2048401.6007447369400.655282531 2047904.0280352  369646.8768295
2047709.10264385369800.7652963562047509.04763694369934.135300964
#Sta/Elev= 30
       0 2761.07       8 2760.71    48.2 2748.03   161.7 2721.93   322.8 2692.95
   366.5 2681.24   392.3 2671.23     407 2668.46   425.4 2661.77   450.9 2656.98
   491.7 2646.15   531.4 2644.19   549.7 2636.45     605 2641.26   632.1 2635.77
   663.3 2635.64  672.142631.281   684.5 2629.33   694.32631.282   704.5 2634.21
   737.1 2636.99   769.9 2646.39   847.3 2654.06   874.9 2664.26   887.8 2672.05
   906.4 2673.66   914.3 2678.24   937.5 2685.58  1013.2 2716.881043.947 2732.86
#Mann= 3 ,-1 , 0
       0      .1       0  672.14    .045       0   694.3      .1       0
Bank Sta=672.14,694.3
XS Rating Curve= 0 ,0
Exp/Cntr(USF)=0,0
Exp/Cntr=0.3,0.1

Type RM Length L Ch R = 1 ,6708    ,383.2,383.2,383.2
XS GIS Cut Line= 3
2048139.99035105369113.3968110672047519.30686806369431.432975902
2047211.52993435369641.747213938
#Sta/Elev= 30
       0 2714.13    16.4 2705.55    43.4 2707.51   61.752703.742   101.2 2700.28
   145.4 2678.26   252.3 2659.43   300.2 2646.94   347.3 2638.21   370.3 2630.63
  445.182623.113   503.8  2625.2   553.92621.707     573 2621.51   587.8 2624.39
   613.6 2620.29   672.6 2626.65   726.6 2644.44   743.1    2653   764.3 2657.16
   773.9 2663.52   808.4 2677.13   843.3 2682.11   869.3 2696.53   937.9 2714.81
   968.6 2720.09   995.7 2728.72  1017.8 2741.47    1060 2742.851070.192  2746.8
#Mann= 6 ,-1 , 0
       0      .1       0   61.75      .1       0  445.18      .1       0
   553.9    .045       0     573      .1       0    1060     .06       0
#XS Ineff= 2 , 0
          502.86 2627.88
Permanent Ineff=
       F       F
Bank Sta=553.9,573
XS Rating Curve= 0 ,0
Exp/Cntr(USF)=0,0
Exp/Cntr=0.3,0.1

Type RM Length L Ch R = 1 ,6325    ,195.5,195.5,195.5
XS GIS Cut Line= 4
2047941.21774803368995.2104685222047579.73373938369082.465229229
2047284.72954842369211.2698759872046964.79542583369394.089374612
#Sta/Elev= 30
       0 2693.97    29.9 2693.01      57 2681.96   107.5 2653.68     121 2655.19
   137.9 2652.58   188.5 2634.61   218.9 2628.36     310 2620.44   328.7 2616.98
   408.4 2616.01   442.3 2613.09   460.2 2614.71  479.612606.268   491.8 2604.75
  501.712606.269   524.6 2611.16   614.1 2619.56   682.2 2634.67   693.8 2630.79
   704.2 2636.93   724.9 2640.21   741.3 2646.65     761 2647.43   783.5 2644.99
   806.2 2656.28   832.7 2662.54   976.2 2690.09  1051.8 2699.211062.248 2704.52
#Mann= 3 ,-1 , 0
       0      .1       0  479.61    .045       0  501.71      .1       0
Bank Sta=479.61,501.71
XS Rating Curve= 0 ,0
Exp/Cntr(USF)=0,0
Exp/Cntr=0.5,0.3

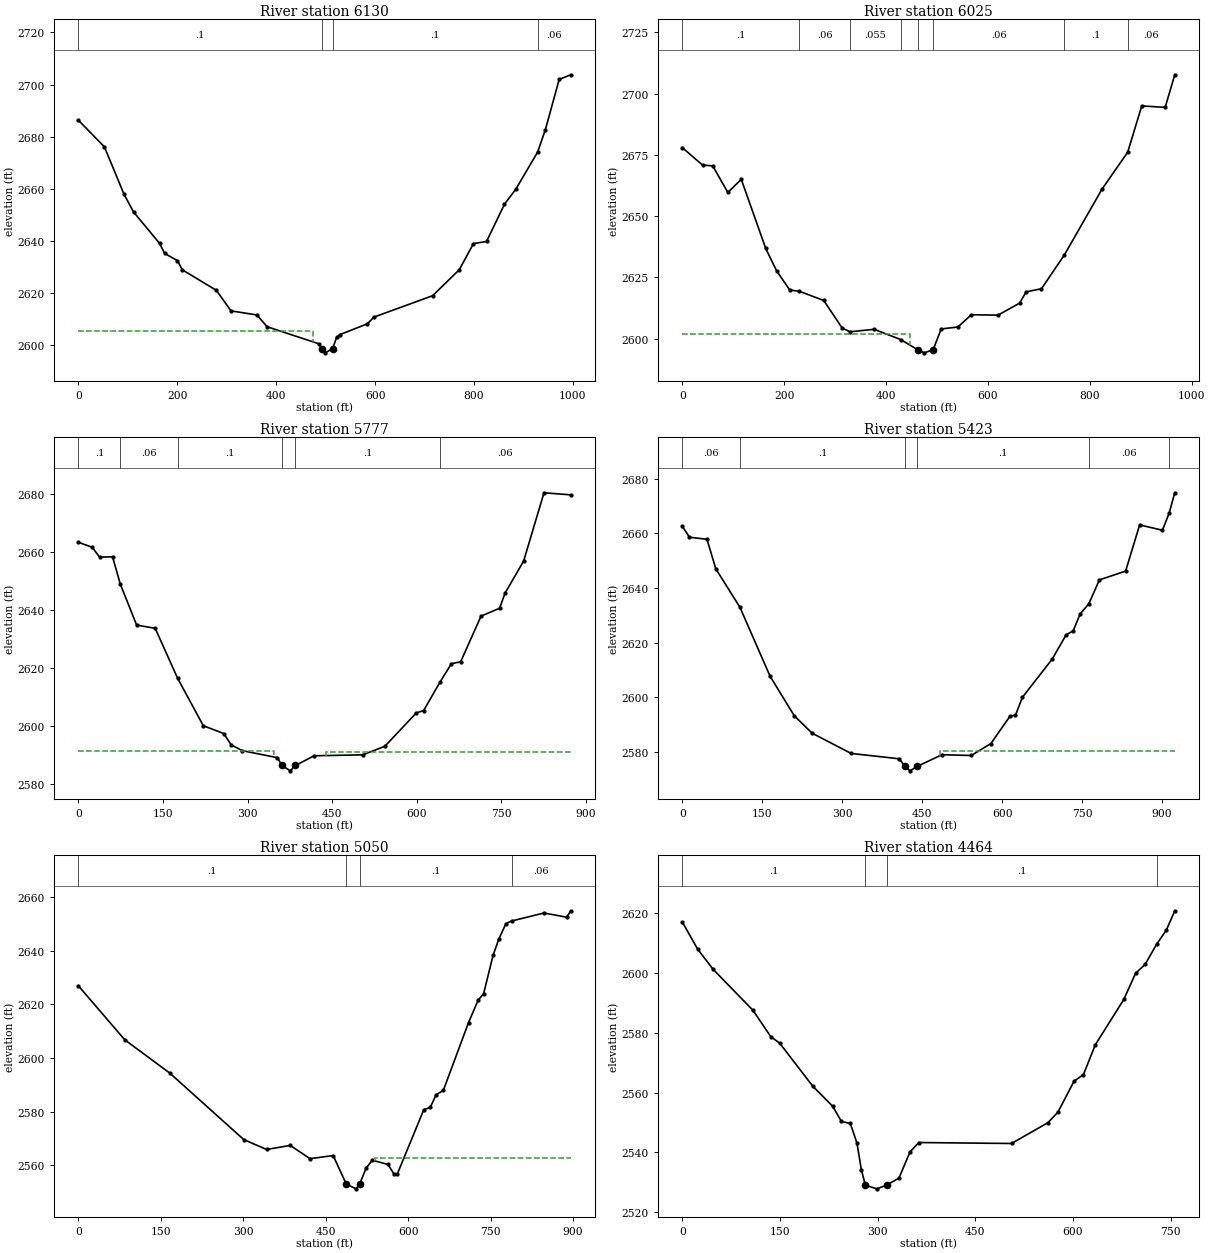
Type RM Length L Ch R = 1 ,6130    ,104.7,104.7,104.7
XS GIS Cut Line= 4
2047866.42795313368957.8155710762047467.54904705368961.970559681
2047247.33465097368974.4355254972046873.38567652369015.985411548
#Sta/Elev= 30
       0 2686.32    52.7 2676.08    92.1 2657.97   111.7 2651.03   164.2 2639.02
   174.4 2635.17   200.3 2632.38   210.2 2628.85   279.1 2620.97   308.6 2613.09
   361.1 2611.51   381.6    2607   485.9 2600.47  492.732598.573   499.1 2596.97
  513.972598.573   522.2 2602.87   528.6 2603.96   584.4 2608.12   597.6 2610.69
   716.4 2618.92   770.2  2628.9   798.9 2638.92   825.3 2639.74   861.6 2654.05
   884.7 2659.88  928.64 2674.09   944.2 2682.65   972.2 2701.99995.7177 2703.76
#Mann= 4 ,-1 , 0
       0      .1       0  492.73    .045       0  513.97      .1       0
  928.64     .06       0
#XS Ineff= 2 , 0
          475.32 2605.23
Permanent Ineff=
       F       F
Bank Sta=492.73,513.97
XS Rating Curve= 0 ,0
Exp/Cntr(USF)=0,0
Exp/Cntr=0.5,0.3

Type RM Length L Ch R = 1 ,6025    ,247.7,247.7,247.7
XS GIS Cut Line= 4
2047804.10312406368820.7009471082047376.13929773368870.560810369
2047164.23487887368870.5608103692046840.14576767368866.405821764
#Sta/Elev= 30
       0 2677.95    39.8 2670.84    59.7 2670.52    89.4 2659.66   115.8 2665.02
   163.8  2636.8   185.2 2627.65   210.9 2619.86  229.942619.304   277.7 2615.57
     314 2604.28  329.372602.794   376.7 2603.79   428.82599.613  461.842595.493
   475.4 2594.19  492.562595.493   508.3 2603.95   541.2 2604.74   567.4 2609.74
   619.9 2609.58   662.2 2614.47   675.1 2619.08   705.2 2620.37  749.872634.074
   824.1 2661.03  874.422676.083   902.1    2695     948 2694.38966.8787  2707.7
#Mann= 8 ,-1 , 0
       0      .1       0  229.94     .06       0  329.37    .055       0
   428.8     .06       0  461.84    .045       0  492.56     .06       0
  749.87      .1       0  874.42     .06       0
#XS Ineff= 2 , 0
          446.75 2601.76
Permanent Ineff=
       F       F
Bank Sta=461.84,492.56
XS Rating Curve= 0 ,0
Exp/Cntr(USF)=0,0
Exp/Cntr=0.5,0.3

Type RM Length L Ch R = 1 ,5777    ,354,354,354
XS GIS Cut Line= 4
2047716.84836335368642.0364370892047421.84417239368629.571471273
2047180.85483329368625.4164826682046844.30075628368617.106505458
#Sta/Elev= 30
       0 2663.37    24.5 2661.65    37.7 2658.24    60.6 2658.36    74.4 2648.92
   103.3 2634.79   136.2 2633.67  175.812616.477   221.5 2600.03   257.7 2597.35
   270.8 2593.45   290.5 2591.43   352.9    2589   360.82586.311   375.8 2584.46
   384.72586.308     418 2589.66   503.8 2589.98   543.2 2592.91     599 2604.45
   612.1 2605.29  640.722614.991   661.3 2621.44   677.7 2622.12   713.8 2637.88
   746.6 2640.58   756.5 2645.87   789.3 2656.88   825.4 2680.46872.9492 2679.74
#Mann= 6 ,-1 , 0
       0      .1       0    74.4     .06       0  175.81      .1       0
   360.8    .045       0   384.7      .1       0  640.72     .06       0
#XS Ineff= 2 , 0
          346.32 2591.35  438.96         2591.08
Permanent Ineff=
       F       F
Bank Sta=360.8,384.7
XS Rating Curve= 0 ,0
Exp/Cntr(USF)=0,0
Exp/Cntr=0.3,0.1

Type RM Length L Ch R = 1 ,5423    ,373,373,373
XS GIS Cut Line= 4
 2047679.4534659368263.9324740242047371.98430913368288.862405655
2047089.44508398368305.4823600752046757.04599557368313.792337286
#Sta/Elev= 30
       0 2662.65    13.4 2658.63    46.3 2657.89    62.8 2647.08   108.22632.918
   164.8 2607.62   210.1 2593.17   243.6 2586.78   316.8 2579.36   406.9  2577.4
  417.632574.655   427.2 2572.98  441.222574.656   487.1 2578.88   542.5 2578.61
   579.1    2583   615.2 2593.11   625.1 2593.36   638.2 2599.97     694 2613.94
   720.3 2622.89   733.4 2624.29   746.5 2630.52  762.73 2634.22   782.6 2642.99
   831.8 2646.22   858.1 2663.15   900.8  2661.2  913.392667.412924.0087 2674.93
#Mann= 6 ,-1 , 0
       0     .06       0   108.2      .1       0  417.63    .045       0
  441.22      .1       0  762.73     .06       0  913.39      .1       0
#XS Ineff= 2 , 0
                          483.98         2580.27
Permanent Ineff=
       F       F
Bank Sta=417.63,441.22
XS Rating Curve= 0 ,0
Exp/Cntr(USF)=0,0
Exp/Cntr=0.3,0.1

Type RM Length L Ch R = 1 ,5050    ,586.3,586.3,586.3
XS GIS Cut Line= 4
2047455.08408123367686.3890579152047135.14995864367939.843362826
 2046939.8654942368114.3528842412046723.80608673368180.832701922
#Sta/Elev= 30
       0    2627    84.4 2606.82   166.1 2594.42     301 2569.54   342.5 2565.85
   385.6 2567.36   421.6 2562.41   463.7 2563.58  487.512552.918   505.3 2551.15
  511.912552.919   523.3 2558.75   534.8 2561.84   563.6 2560.25   574.2 2556.67
   580.5 2556.75   628.6 2580.74   640.3 2581.54   650.9 2586.27   664.1  2587.9
     710 2613.25   727.2  2621.5   737.5  2624.1   754.6 2638.35   764.9 2644.33
   778.1 2650.24  788.432651.186   847.3 2654.17   888.5  2652.6896.1149    2655
#Mann= 4 ,-1 , 0
       0      .1       0  487.51    .045       0  511.91      .1       0
  788.43     .06       0
#XS Ineff= 2 , 0
                          540.26          2562.7
Permanent Ineff=
       F       F
Bank Sta=487.51,511.91
XS Rating Curve= 0 ,0
Exp/Cntr(USF)=0,0
Exp/Cntr=0.3,0.1

Type RM Length L Ch R = 1 ,4464    ,261.3,261.3,261.3
XS GIS Cut Line= 3
2047288.88453703367520.1895137112046865.07569931367632.374206049
2046578.38148555367769.488830017
#Sta/Elev= 30
       0 2617.06    23.8 2607.92    47.4 2601.22   108.7 2587.47   135.8 2578.71
   149.4 2576.56   200.3 2562.12   230.9 2555.41   244.4  2550.3     258 2549.64
   268.2 2543.07     275 2534.11  281.132528.985   298.7 2527.76  313.582528.984
   332.7 2531.36   349.6 2540.09   363.2 2543.26   505.5 2542.94   561.5 2549.91
   576.9 2553.47   601.5 2563.78     616 2566.01   634.2 2575.98   677.9 2591.14
   696.1 2599.92   710.6 2602.87  728.392609.651   743.3 2614.36 756.201 2620.83
#Mann= 4 ,-1 , 0
       0      .1       0  281.13    .045       0  313.58      .1       0
  728.39     .06       0
Bank Sta=281.13,313.58
XS Rating Curve= 0 ,0
Exp/Cntr(USF)=0,0
Exp/Cntr=0.3,0.1

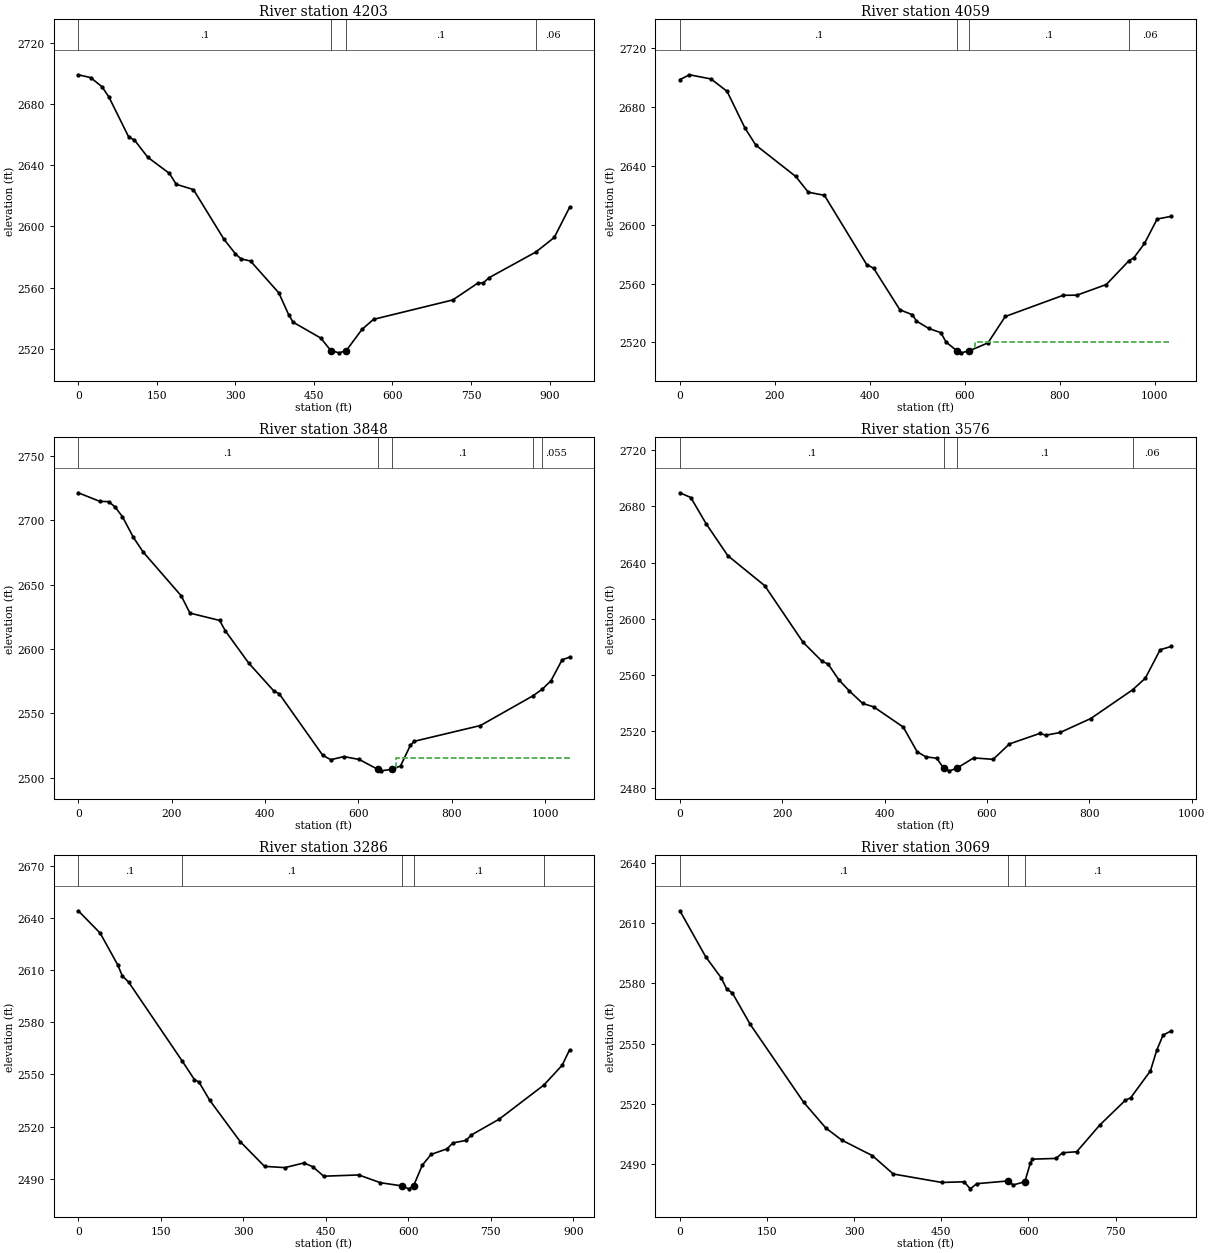
Type RM Length L Ch R = 1 ,4203    ,143.4,143.4,143.4
XS GIS Cut Line= 4
2047280.57455982367183.6354366982046923.24553978367353.989969507
2046711.34112092 367462.01967324 2046453.7318274367624.064228839
#Sta/Elev= 30
       0 2699.05    23.6  2697.2    45.4 2691.19    58.4 2684.57    96.3 2658.35
   107.2 2656.42   132.6 2645.16     174 2634.57   187.1 2627.46   219.9 2624.01
     278 2591.63   299.8 2582.12   310.7 2578.73   328.9 2577.29   382.9  2556.5
   401.7 2542.21   410.2 2537.31     463 2526.96  482.372518.728     498 2517.29
  511.682518.728   541.6 2532.56   563.8 2539.18   715.1 2551.86     763  2562.9
   773.2 2563.02   784.4  2566.4  873.972583.232   908.9  2592.7938.0491  2612.3
#Mann= 4 ,-1 , 0
       0      .1       0  482.37    .045       0  511.68      .1       0
  873.97     .06       0
Bank Sta=482.37,511.68
XS Rating Curve= 0 ,0
Exp/Cntr(USF)=0,0
Exp/Cntr=0.3,0.1

Type RM Length L Ch R = 1 ,4059    ,211.9,211.9,211.9
XS GIS Cut Line= 4
2047247.33465097367017.4358924942046811.06084744367262.580220195
2046553.45155392367391.3848669532046341.54713506367516.034525106
#Sta/Elev= 30
       0 2698.61    20.2 2701.91    65.6 2699.05    99.4 2690.64   136.8 2665.82
   159.9 2654.07   243.9  2632.8   270.4 2622.09   304.2 2619.99   393.3 2572.92
   407.8 2570.46   463.2 2542.19   489.7 2538.79   498.1 2534.54   523.8 2529.53
   549.5 2526.62   560.5 2520.22  583.162514.347   592.2 2512.93  609.692514.348
   648.6 2519.69   685.1 2537.63     807 2552.04   835.8 2552.11   897.8 2559.37
  945.262575.437     956 2577.61   978.2 2587.27  1004.9 2603.891034.294 2605.67
#Mann= 4 ,-1 , 0
       0      .1       0  583.16    .045       0  609.69      .1       0
  945.26     .06       0
#XS Ineff= 2 , 0
                          622.34         2520.27
Permanent Ineff=
       F       F
Bank Sta=583.16,609.69
XS Rating Curve= 0 ,0
Exp/Cntr(USF)=0,0
Exp/Cntr=0.3,0.1

Type RM Length L Ch R = 1 ,3848    ,272,272,272
XS GIS Cut Line= 4
2047155.92490166366826.3064166592046690.56617789 367071.45074436
2046470.35178182367233.4952999592046250.13738575367358.144958112
#Sta/Elev= 30
       0 2721.52    46.3 2714.81    64.9 2714.65    78.4 2710.65    94.5 2702.97
   118.1 2686.81     139 2675.44   220.6 2641.36   239.2 2627.97   302.7 2622.28
   314.8  2614.3   365.2 2589.08   419.3 2567.28   430.3 2565.32   523.7 2517.41
   540.9    2514   569.4  2516.4     602 2514.15  641.552506.512   648.2 2505.33
  672.442506.511   690.4 2509.14   711.5 2525.21   720.1 2528.33   861.7 2540.58
  974.542563.747  994.28 2568.88  1012.7 2575.37  1036.6 2591.681052.434 2593.67
#Mann= 5 ,-1 , 0
       0      .1       0  641.55    .045       0  672.44      .1       0
  974.54     .06       0  994.28    .055       0
#XS Ineff= 2 , 0
                          681.56          2515.2
Permanent Ineff=
       F       F
Bank Sta=641.55,672.44
XS Rating Curve= 0 ,0
Exp/Cntr(USF)=0,0
Exp/Cntr=0.3,0.1

Type RM Length L Ch R = 1 ,3576    ,289.9,289.9,289.9
XS GIS Cut Line= 3
2046869.23068791366577.0071003532046354.01210088367000.815938074
2046113.02276178367167.015482278
#Sta/Elev= 30
       0  2689.7    21.3 2686.33    51.5 2667.55    93.6 2644.99   165.9 2623.59
   240.6 2583.44   277.9 2569.82   289.4 2568.01   310.5 2556.77   331.1 2548.75
   357.3 2539.87   378.6 2537.49   436.4 2523.11   463.5 2505.62   480.5 2501.93
   501.8 2500.94  515.782493.698   526.6 2491.97  540.572493.697   573.9 2501.15
   612.2 2500.16   643.9  2511.1   703.3 2518.58   715.2  2517.3   743.1 2519.24
   802.9 2529.18  884.722549.618   909.5 2557.86   938.4 2578.06959.8737 2580.41
#Mann= 4 ,-1 , 0
       0      .1       0  515.78    .045       0  540.57      .1       0
  884.72     .06       0
Bank Sta=515.78,540.57
XS Rating Curve= 0 ,0
Exp/Cntr(USF)=0,0
Exp/Cntr=0.3,0.1

Type RM Length L Ch R = 1 ,3286    ,216.3,216.3,216.3
XS GIS Cut Line= 2
2046711.34112092366423.2725219642045975.90813781366930.181131787
#Sta/Elev= 30
       0 2644.41    39.8 2631.52    71.7 2613.21    80.1 2606.82    91.6 2603.25
   188.7 2557.88   211.1  2547.1   219.5  2545.6     239 2535.12   294.7 2511.19
   338.6 2497.02   375.6  2496.3   410.4    2499   426.3 2496.81   446.2 2491.35
     510 2492.07   549.5 2487.58  588.072485.776   601.1 2484.06  609.612485.775
   625.5 2497.71   641.5 2503.91   670.5 2507.14   681.3 2510.56   705.2    2512
   714.6 2515.11     765 2524.18   846.7 2543.94   879.8 2555.33893.2066 2564.16
#Mann= 5 ,-1 , 0
       0      .1       0   188.7      .1       0  588.07    .045       0
  609.61      .1       0   846.7     .06       0
Bank Sta=588.07,609.61
XS Rating Curve= 0 ,0
Exp/Cntr(USF)=0,0
Exp/Cntr=0.3,0.1

Type RM Length L Ch R = 1 ,3069    ,418.6,418.6,418.6
XS GIS Cut Line= 4
 2046614.8615093366285.0455341952046197.51122315366537.092373673
2046035.48111206366620.5624309022045909.45769232366743.312515064
#Sta/Elev= 30
       0 2616.25    44.4 2593.33    71.2 2582.78    80.5 2577.29    90.4 2575.24
     121 2559.67     213 2520.82   251.3 2507.91   278.8  2501.9   331.4 2494.17
   367.3 2485.03   450.9  2480.8   489.2 2481.13     500 2477.62   511.1 2480.19
   564.7 2481.55   573.8 2479.56   593.9 2481.15   603.3 2490.48     607 2492.42
   647.6 2492.79   658.7 2495.61   683.2 2496.11   722.8 2509.41   766.9 2521.78
   776.1 2523.02   810.1 2536.45   820.9  2546.7   831.8 2554.25   845.7 2556.35
#Mann= 3 , 0 , 0
       0      .1       0   564.7    .045       0   593.9      .1       0
Bank Sta=564.7,593.9
XS Rating Curve= 0 ,0
Exp/Cntr(USF)=0,0
Exp/Cntr=0.3,0.1

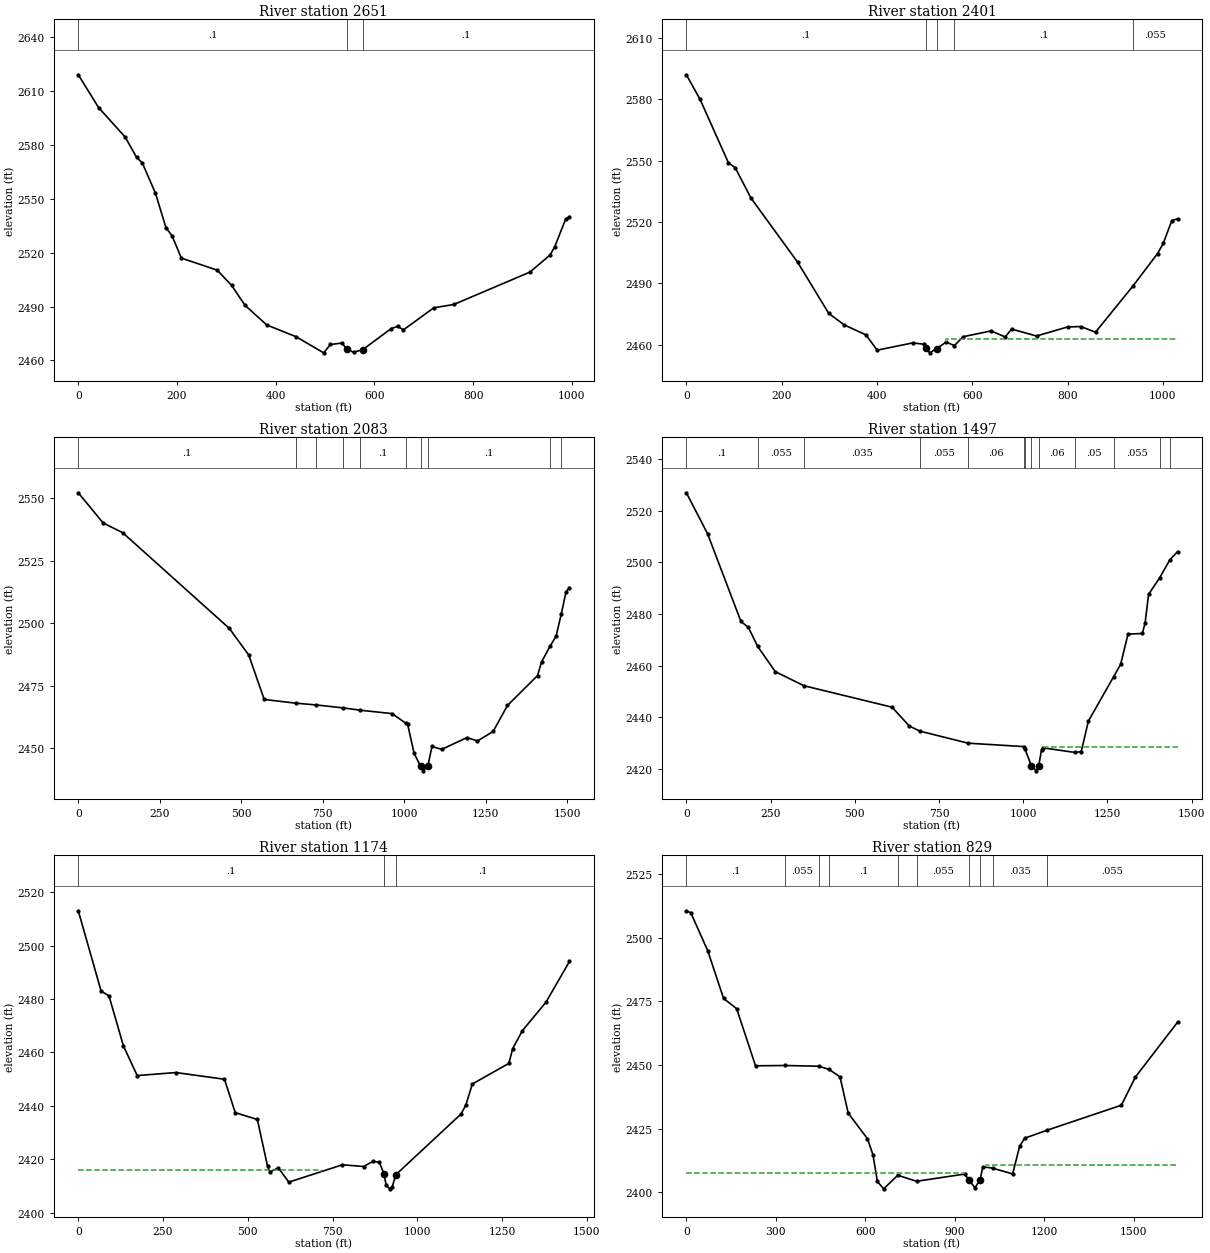
Type RM Length L Ch R = 1 ,2651    ,250,250,250
XS GIS Cut Line= 4
2046474.10807946365954.4386408552046071.48780342366201.575476966
 2045883.2710077 366347.238910172045686.87087304366553.459051561
#Sta/Elev= 30
       0  2619.2    41.1 2600.95      95 2584.47   118.1 2573.17   129.6 2570.11
   156.4 2553.16   177.8 2533.82   189.8 2529.53   208.9 2517.01   281.5 2510.29
   310.6 2501.79   337.9 2490.69   381.8 2479.75   441.5 2473.17     497  2464.2
     511 2468.85   534.4 2469.66   543.8 2466.33   557.8  2464.5   576.5    2466
     634 2477.71   646.9 2478.96   658.9 2477.01   720.2 2489.28   760.9 2491.16
     915 2509.19   955.8 2518.68   965.4 2523.35   987.5 2538.76   995.2 2540.13
#Mann= 3 , 0 , 0
       0      .1       0   543.8    .045       0   576.5      .1       0
Bank Sta=543.8,576.5
XS Rating Curve= 0 ,0
Exp/Cntr(USF)=0,0
Exp/Cntr=0.3,0.1

Type RM Length L Ch R = 1 ,2401    ,317.8,317.8,317.8
XS GIS Cut Line= 4
2046341.54713506365808.3342084092046025.76800107365957.913798193
2045739.07378732366144.8882854232045481.46449381366365.102681493
#Sta/Elev= 30
       0 2591.99    28.8 2579.96    88.1 2549.05   102.7 2546.51   135.3 2531.83
   233.6 2500.34   298.7 2475.39   331.3 2469.74   376.9 2464.84   400.4  2457.4
   474.8 2460.94   498.4 2460.31   503.1 2458.27   510.5 2456.09   524.92458.139
   545.4 2461.35  562.392459.638   580.6 2463.96   639.4  2466.8   669.1 2463.85
   682.4 2467.71   734.7 2464.32   799.8 2468.73   827.2 2468.94   858.5  2466.2
  936.592488.621   988.7 2504.61  1000.9 2509.71  1018.6 2520.731030.596 2521.54
#Mann= 5 ,-1 , 0
       0      .1       0   503.1    .045       0   524.9      .1       0
  562.39      .1       0  936.59    .055       0
#XS Ineff= 2 , 0
                          545.45         2463.06
Permanent Ineff=
       F       F
Bank Sta=503.1,524.9
XS Rating Curve= 0 ,0
Exp/Cntr(USF)=0,0
Exp/Cntr=0.3,0.1

Type RM Length L Ch R = 1 ,2083    ,585.7,585.7,585.7
XS GIS Cut Line= 4
 2046210.0658549365024.7433684892045674.94487245 365819.01099024
2045621.09622013365990.6535695172045409.06715161366293.552238829
#Sta/Elev= 30
       0 2552.25    76.2 2540.18   136.2  2536.3   463.8 2497.98   523.2 2487.34
   570.6  2469.6  666.672468.128  730.892467.398  811.812466.249  863.862465.319
     963 2463.95 1006.192459.995  1010.7 2459.74  1030.5 2448.05 1050.592442.929
    1058 2441.06 1072.682442.927  1085.5 2450.81  1115.4 2449.65    1193 2454.37
  1225.1 2453.01  1273.1 2456.81  1317.2 2467.21  1409.3 2479.14  1421.8 2484.62
 1448.552491.069  1466.3 2494.85 1482.172503.755  1496.9 2512.68 1507.34 2514.26
#Mann= 10 ,-1 , 0
       0      .1       0  666.67    .055       0  730.89      .1       0
  811.81     .06       0  863.86      .1       0 1006.19      .1       0
 1050.59    .045       0 1072.68      .1       0 1448.55    .055       0
 1482.17     .06       0
Bank Sta=1050.59,1072.68
XS Rating Curve= 0 ,0
Exp/Cntr(USF)=0,0
Exp/Cntr=0.3,0.1

Type RM Length L Ch R = 1 ,1497    ,323,323,323
XS GIS Cut Line= 4
2045596.19860508364739.9004329932045166.84978255365589.364770036
2045092.98331846365718.6310821952044885.23388821366009.480284552
#Sta/Elev= 30
       0 2526.86    62.8 2511.08     162 2477.12   184.1 2474.81  211.392467.528
   264.1 2457.69  348.912452.264   610.9 2443.95     662 2436.64  693.67 2434.69
  836.292430.046 1001.712428.729 1004.732427.921 1024.212421.377  1039.3 2419.35
 1046.062421.376  1054.4 2427.45  1058.2 2428.26 1153.372426.457  1172.3 2426.78
  1193.5 2438.58  1268.72455.802  1289.2 2460.52  1311.1 2472.18  1353.7 2472.48
  1361.8 2476.46  1372.2 2487.58 1405.192494.008 1435.532500.9761458.112 2504.08
#Mann= 13 ,-1 , 0
       0      .1       0  211.39    .055       0  348.91    .035       0
  693.67    .055       0  836.29     .06       0 1001.71    .055       0
 1004.73     .06       0 1024.21    .045       0 1046.06     .06       0
 1153.37     .05       0  1268.7    .055       0 1405.19     .06       0
 1435.53      .1       0
#XS Ineff= 2 , 0
                         1061.13         2428.38
Permanent Ineff=
       F       F
Bank Sta=1024.21,1046.06
XS Rating Curve= 0 ,0
Exp/Cntr(USF)=0,0
Exp/Cntr=0.3,0.1

Type RM Length L Ch R = 1 ,1174    ,345.3,345.3,345.3
XS GIS Cut Line= 4
2045350.28738209364696.2121813942044885.19570627 365438.26856303
2044791.13222127 365600.266787192044589.94087837365929.488984677
#Sta/Elev= 30
       0 2513.01    67.3 2482.96    90.6 2481.15   133.1 2462.45   173.8 2451.34
     288 2452.47   431.3 2449.96     463 2437.46   528.1 2434.91   558.2 2417.52
   565.3 2415.25     590 2416.82     621 2411.46   779.2 2417.95   841.7 2417.31
   868.8  2419.2   887.9 2418.93   901.4 2414.69   908.4 2410.24   918.3 2408.95
   925.9 2409.66     937 2414.27  1128.8 2436.92  1143.2 2440.27  1162.4 2448.19
  1270.1 2455.89  1281.5 2461.43  1310.2 2468.17  1379.4 2478.75  1448.9 2494.04
#Mann= 3 , 0 , 0
       0      .1       0   901.4    .045       0     937      .1       0
#XS Ineff= 2 , 0
          715.42 2416.16
Permanent Ineff=
       F       F
Bank Sta=901.4,937
XS Rating Curve= 0 ,0
Exp/Cntr(USF)=0,0
Exp/Cntr=0.3,0.1

Type RM Length L Ch R = 1 ,829     ,248.4,248.4,248.4
XS GIS Cut Line= 4
2045198.51407614364514.8179684262044634.88965021365198.766710006
  2044527.231052 365376.086754122044204.25525736365825.719723122
#Sta/Elev= 30
       0 2510.57    14.8 2509.81    71.6 2494.91   124.8 2476.16   168.7 2472.13
     232 2449.68  331.942449.805  444.642449.515  478.692448.247   515.3 2445.35
   542.8 2431.11   607.3 2421.04   625.9 2414.75   640.6 2404.26   661.8 2401.36
  709.042406.694  772.182404.327   933.1 2407.16   948.5  2404.8   967.7 2401.78
   984.9 2404.79   994.4 2410.02 1026.852409.481  1094.4 2407.23  1117.7 2418.05
  1134.6 2421.24 1209.372424.365  1459.1 2434.21  1506.1 2445.291647.313 2466.79
#Mann= 10 ,-1 , 0
       0      .1       0  331.94    .055       0  444.64      .1       0
  478.69      .1       0  709.04     .06       0  772.18    .055       0
   948.5    .045       0   984.9    .055       0 1026.85    .035       0
 1209.37    .055       0
#XS Ineff= 2 , 0
          932.07 2407.45 1003.64         2410.81
Permanent Ineff=
       F       F
Bank Sta=948.5,984.9
XS Rating Curve= 0 ,0
Exp/Cntr(USF)=0,0
Exp/Cntr=0.3,0.1