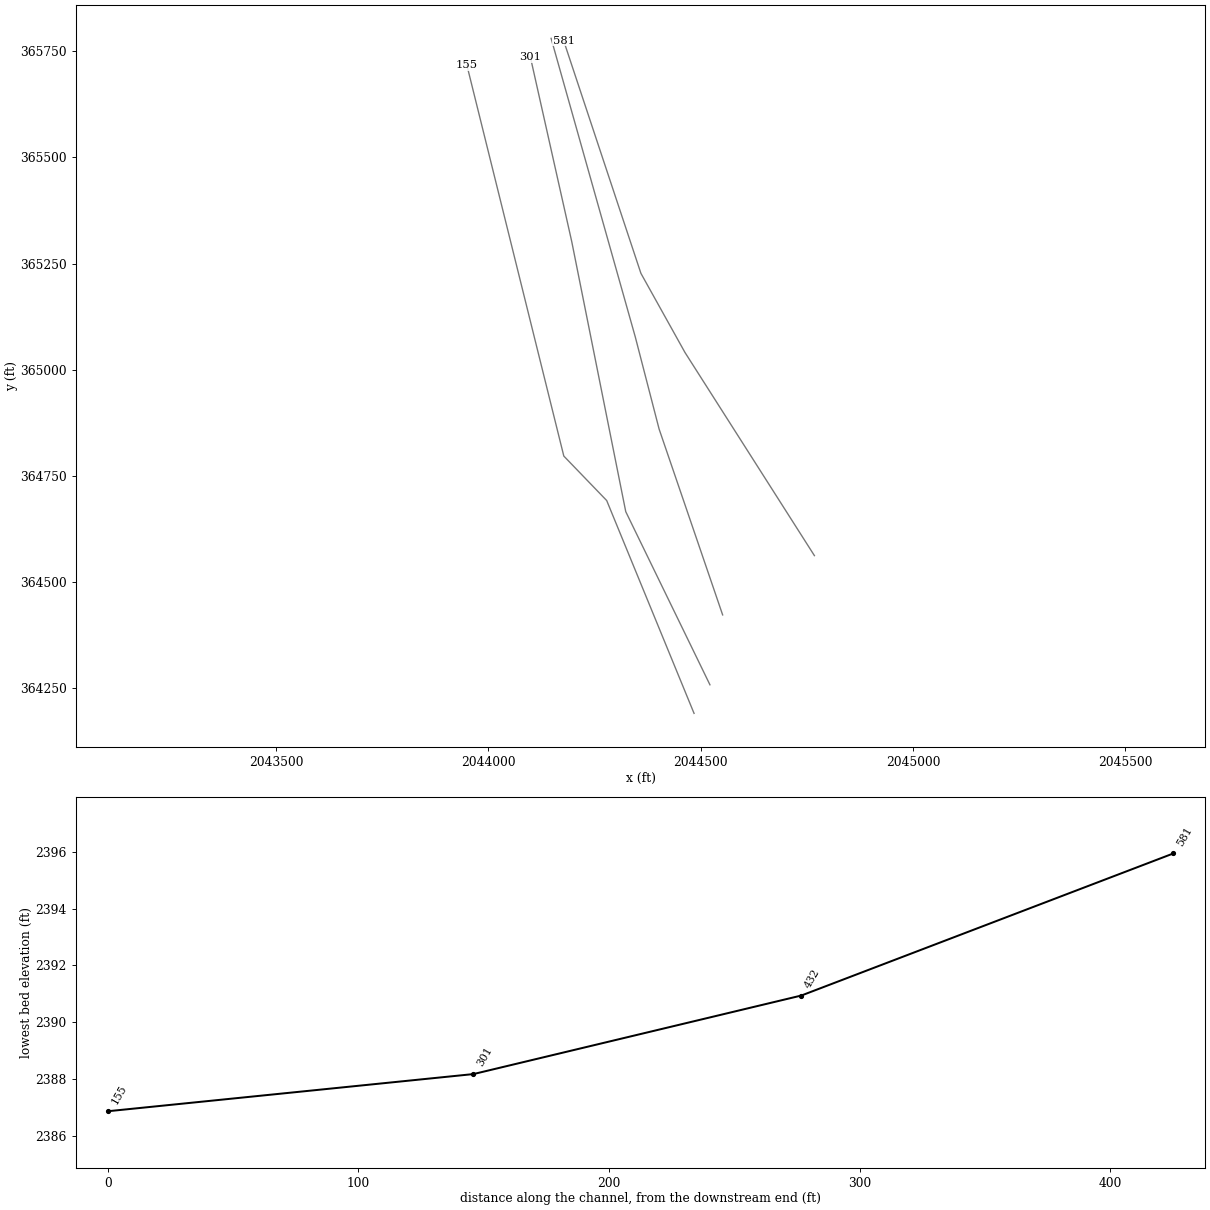
HEC-RAS study LAURELCK1.prj: LAURELCK1

--- LAURELCK1.g01 (geometry) --- (continued)

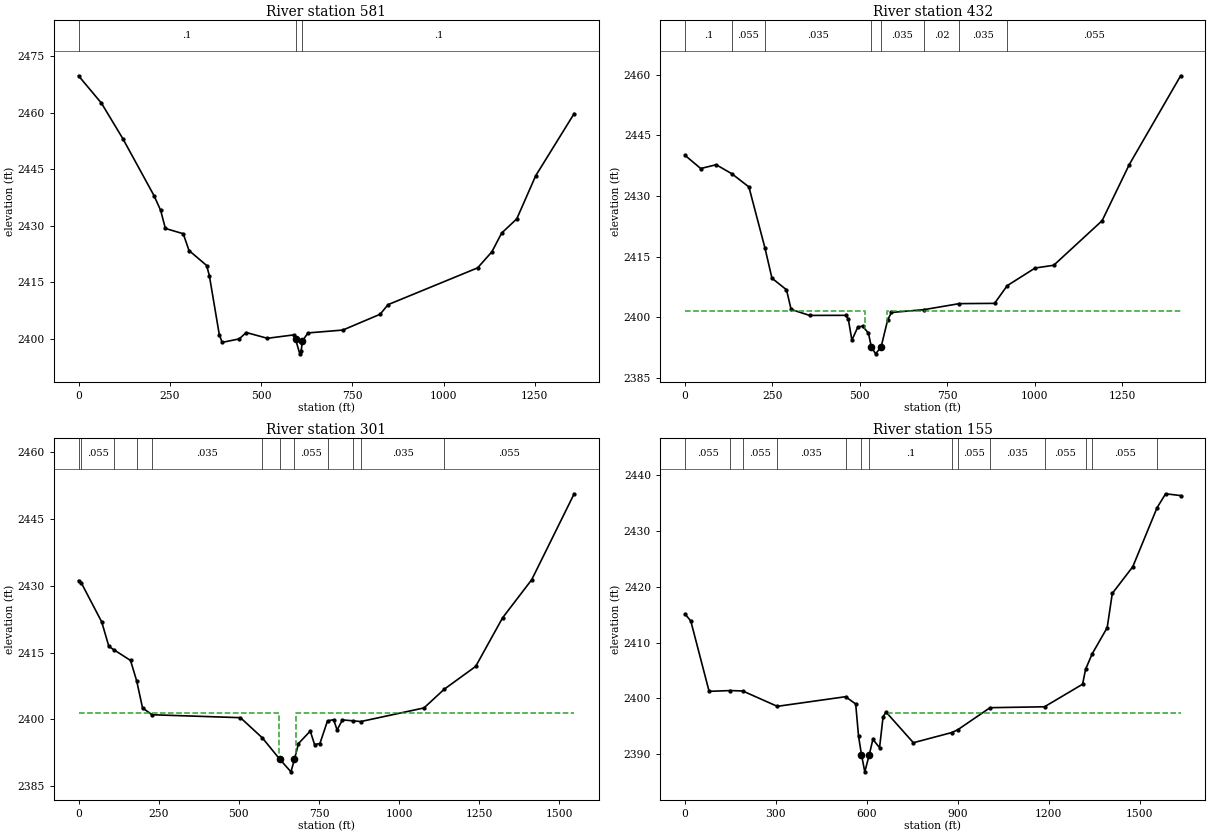
Type RM Length L Ch R = 1 ,581     ,148.5,148.5,148.5
XS GIS Cut Line= 4
 2044767.7731225364562.4591314792044463.00743111365040.771952684
2044359.30243891365227.0176529762044177.28959544365775.172611791
#Sta/Elev= 30
       0 2469.87    62.8  2462.6   121.2 2453.19   206.8 2438.02   225.1 2434.08
   237.9 2429.29   286.9 2427.88   302.7 2423.42   351.1 2419.43   358.5 2416.71
   385.7 2401.05   393.5 2398.99   440.2 2399.92   459.6 2401.62   517.4 2400.08
     589 2400.98   594.8  2399.8   606.1 2395.95   609.8 2396.64   613.6 2399.41
   628.6 2401.51   724.1 2402.27   826.2 2406.47   848.1 2409.03  1093.5 2418.81
  1132.5 2423.08  1159.2 2428.05  1200.7 2431.84  1252.5 2443.29  1357.9 2459.82
#Mann= 3 , 0 , 0
       0      .1       0   594.8    .045       0   613.6      .1       0
Bank Sta=594.8,613.6
XS Rating Curve= 0 ,0
Exp/Cntr(USF)=0,0
Exp/Cntr=0.3,0.1

Type RM Length L Ch R = 1 ,432     ,130.9,130.9,130.9
XS GIS Cut Line= 4
2044551.71749353364422.8947509292044402.13790375364860.415051046
2044346.04555758365077.3054562322044147.85260112365780.329528215
#Sta/Elev= 30
       0 2440.03      45 2436.76    89.1  2437.7  133.932435.467   182.7 2432.21
  228.692417.087   248.6 2409.65   290.2 2406.77   303.4 2401.92   356.1 2400.44
   460.1 2400.46   466.9 2399.51   477.1 2394.32     494 2397.54   507.6 2397.82
   524.5 2396.05  532.742392.638   544.9 2390.94  560.622392.637   579.4 2399.33
   590.2 2401.17  682.71 2401.86  783.992403.351   884.9 2403.42  921.112407.794
  1000.9 2412.16  1054.1 2412.84  1192.4 2423.86  1270.1 2437.751416.836 2459.69
#Mann= 8 ,-1 , 0
       0      .1       0  133.93    .055       0  228.69    .035       0
  532.74    .045       0  560.62    .035       0  682.71     .02       0
  783.99    .035       0  921.11    .055       0
#XS Ineff= 2 , 0
             515  2401.5     577          2401.5
Permanent Ineff=
       F       F
Bank Sta=532.74,560.62
XS Rating Curve= 0 ,0
Exp/Cntr(USF)=0,0
Exp/Cntr=0.5,0.3

Type RM Length L Ch R = 1 ,301     ,145.9,145.9,145.9
XS GIS Cut Line= 4
2044521.80157558364258.3572021672044323.60861911364665.961584327
 2044196.4659678365301.6748409082044099.23923444 365735.45565128
#Sta/Elev= 30
       0 2431.18    9.012430.617    72.4 2421.88    94.6 2416.39  110.452415.617
   162.2 2413.22  181.552408.595   199.7 2402.55  229.19 2401.01   505.1 2400.35
  573.732395.787  628.29 2390.96   662.7 2388.17  673.432390.962   686.1 2394.53
   722.9 2397.34   736.3 2394.31     753 2394.54  776.662399.622   795.7  2399.9
   806.6 2397.59   823.3 2399.85  857.012399.637  880.542399.481  1077.6 2402.54
 1140.842406.751  1238.9 2411.88  1322.9 2422.82  1413.7 2431.381546.081  2450.7
#Mann= 12 ,-1 , 0
       0      .1       0    9.01    .055       0  110.45      .1       0
  181.55    .055       0  229.19    .035       0  573.73    .055       0
  628.29    .045       0  673.43    .055       0  776.66    .035       0
  857.01    .055       0  880.54    .035       0 1140.84    .055       0
#XS Ineff= 2 , 0
             625  2401.5     678          2401.5
Permanent Ineff=
       F       F
Bank Sta=628.29,673.43
XS Rating Curve= 0 ,0
Exp/Cntr(USF)=0,0
Exp/Cntr=0.5,0.3

Type RM Length L Ch R = 1 ,155     ,142,142,142
XS GIS Cut Line= 4
2044484.40667813364191.0463867642044278.73474218364692.138012539
2044177.76851907364796.8437253882043949.65964465365716.758202557
#Sta/Elev= 30
       0 2415.11    19.1 2413.86    79.6 2401.26  149.882401.402  190.492401.326
  304.46 2398.58  529.742400.303   563.1    2399   572.5 2393.24  582.242389.921
   593.1 2386.86  607.922389.923   619.8 2392.67   641.8 2391.18   653.4 2396.69
     663 2397.57   753.4 2392.07  880.462393.896  900.512394.417 1006.292398.337
 1185.88  2398.5  1311.5 2402.54  1321.5 2405.24 1343.362407.994  1392.6 2412.65
  1409.5 2418.79  1477.1 2423.56 1557.182434.121  1585.3 2436.611634.889 2436.29
#Mann= 14 ,-1 , 0
       0    .055       0  149.88     .06       0  190.49    .055       0
  304.46    .035       0  529.74      .1       0  582.24    .045       0
  607.92      .1       0  880.46     .06       0  900.51    .055       0
 1006.29    .035       0 1185.88    .055       0  1321.5    .035       0
 1343.36    .055       0 1557.18     .06       0
#XS Ineff= 2 , 0
                          673.25         2397.43
Permanent Ineff=
       F       F
Bank Sta=582.24,607.92
XS Rating Curve= 0 ,0
Exp/Cntr(USF)=0,0
Exp/Cntr=0.3,0.1
Stream Node=BIGCLEARCK      ,Main            , 0 , 0 ,Upstream end
Stream Node=BIGCLEARCK      ,Main            , 0 , 1 ,Downstream end
Stream Node=BROADRN         ,Main            , 0 , 0 ,Upstream end
Stream Node=BROADRN         ,Main            , 0 , 1 ,Downstream end
Stream Node=LAURELBR        ,Main            , 0 , 0 ,Upstream end
Stream Node=LAURELBR        ,Main            , 0 , 1 ,Downstream end
Stream Node=LAURELCK1       ,Main            , 0 , 0 ,Upstream end
Stream Node=LAURELCK1       ,Main            , 0 , 1 ,Downstream end
Stream Node=MEADOWRV3       ,Main            , 0 , 0 ,Upstream end
Stream Node=MEADOWRV3       ,Main            , 0 , 1 ,Downstream end
Stream Node=MEADOWRV4       ,Main            , 0 , 0 ,Upstream end
Stream Node=MEADOWRV4       ,Main            , 0 , 1 ,Downstream end
Stream Node=MLGNCK          ,Main            , 0 , 0 ,Upstream end
Stream Node=MLGNCK          ,Main            , 0 , 1 ,Downstream end
Stream Node=MLGNCKTR3       ,Main            , 0 , 0 ,Upstream end
Stream Node=MLGNCKTR3       ,Main            , 0 , 1 ,Downstream end
Stream Node=MLGNCKTR4       ,Main            , 0 , 0 ,Upstream end
Stream Node=MLGNCKTR4       ,Main            , 0 , 1 ,Downstream end
Stream Node=MUDDYCK         ,Main            , 0 , 0 ,Upstream end
Stream Node=MUDDYCK         ,Main            , 0 , 1 ,Downstream end
Stream Node=SECONDCK        ,Main            , 0 , 0 ,Upstream end
Stream Node=SECONDCK        ,Main            , 0 , 1 ,Downstream end
Stream Node=TUCKHORN        ,Main            , 0 , 0 ,Upstream end
Stream Node=TUCKHORN        ,Main            , 0 , 1 ,Downstream end
Stream Node=TUCKHORNT2      ,Main            , 0 , 0 ,Upstream end
Stream Node=TUCKHORNT2      ,Main            , 0 , 1 ,Downstream end
LCMann Table=0

Chan Stop Cuts=-1
Use User Specified Reach Order=0
Composite Channel Slope=5